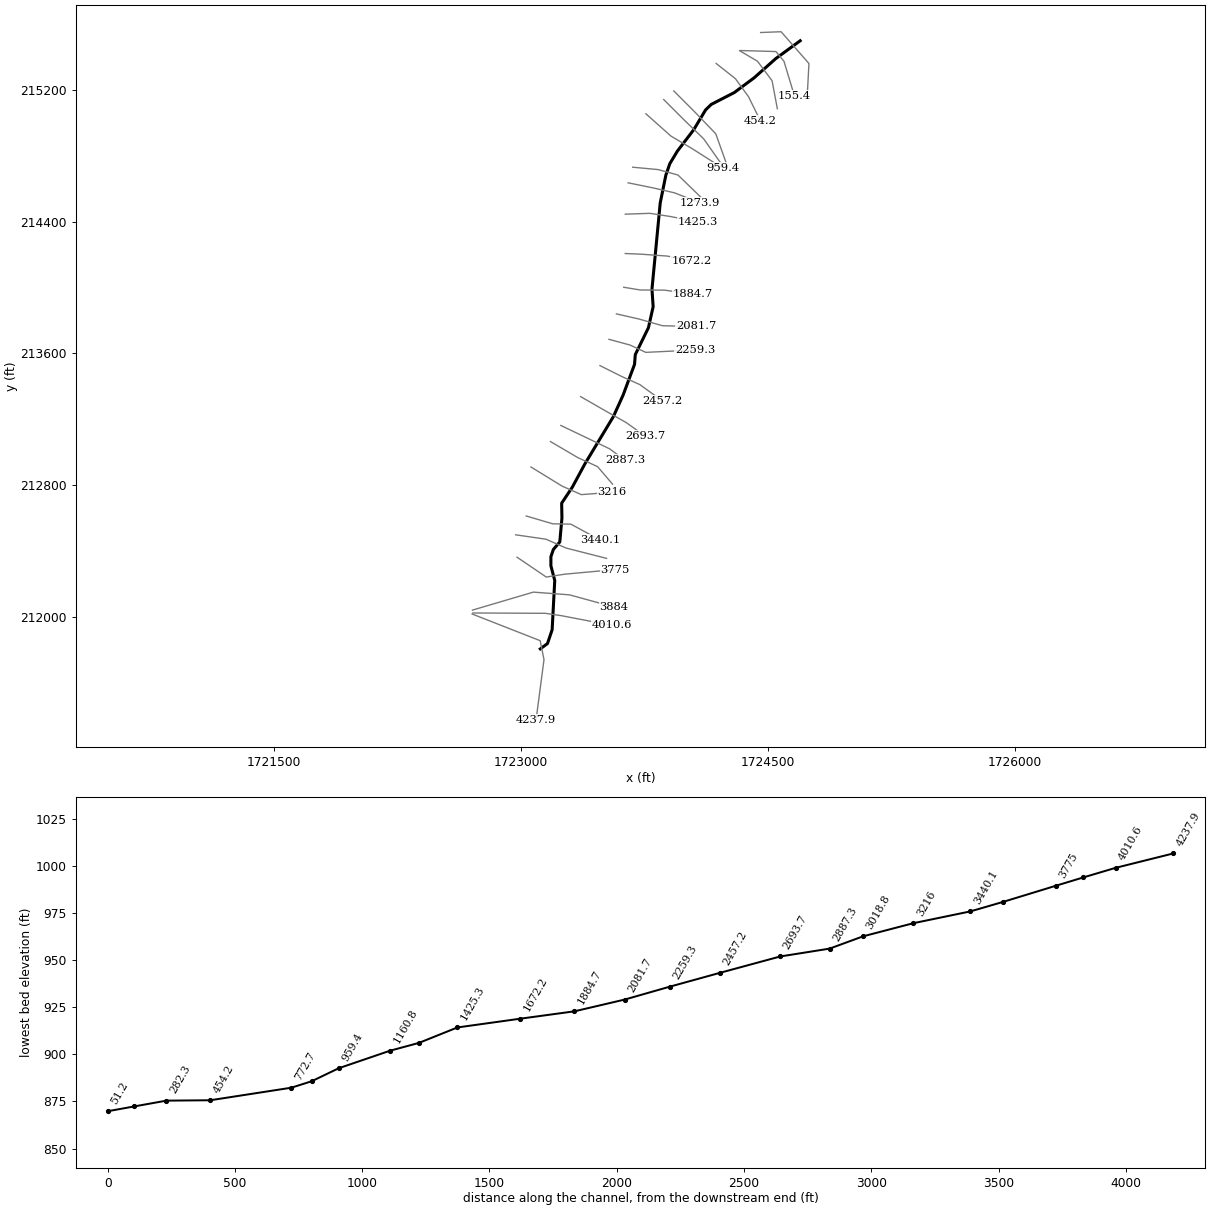
--- whtkbrnch.prj (project) ---

Proj Title=whtkbrnch
Current Plan=p01
Default Exp/Contr=0,0
English Units
Geom File=g01
Flow File=f01
Plan File=p01
BEGIN DESCRIPTION:
END DESCRIPTION:
DSS Export Rating Curves= 0
DSS Export Rating Curve Sorted= 0
DSS Export Volume Flow Curves= 0
DXF OffsetX= 0
DXF OffsetY= 0
DXF ScaleX= 0
DXF ScaleY= 0

--- whtkbrnch.p01 (plan) ---

Plan Title=Floodplain
Program Version=4.00
Geom File=g01
Flow File=f01
K Sum by GR=0
Std Step Tol=0.01
Critical Tol=0.01
Num of Std Step Trials=20
Max Error Tol=0.3
Flow Tol Ratio=0.001
Split Flow NTrial=30
Split Flow Tol=0.02
Split Flow Ratio=0.02
Log Output Level=0
Friction Slope Method=1
Unsteady Friction Slope Method=2
Unsteady Bridges Friction Slope Method=1
Global Log Level=0
CheckData=False
Run HTab=0
Run UNet=0
Run PostProcess=0
UNET Theta=0
UNET Theta Warmup=0
UNET ZTol=0
UNET ZSATol=0
UNET MxIter=0
UNET MaxInSteps=0
UNET DtIC=0
UNET DtMin=0
UNET MaxCRTS=0
UNET WFStab=0
UNET SFStab=0
UNET WFX=0
UNET SFX=0
UNET DSS MLevel=0
UNET DZMax Abort=0
UNET Convert EG Bridges=0
UNET Use Existing IB Tables=0
UNET Froude Limit=0
UNET Froude Power=0
Write IC File=0
Echo Input=False
Echo Output=False
Write Detailed=0

--- whtkbrnch.f01 (steady flow) ---

Flow Title=NFF Regression Equation
Program Version=4.00
Number of Profiles= 1
Profile Names=P100yr
River Rch & RM=whtkbrnch,Main            ,4237.9
     385
River Rch & RM=whtkbrnch,Main            ,4010.6
     387
River Rch & RM=whtkbrnch,Main            ,3569.1
     407
River Rch & RM=whtkbrnch,Main            ,2081.7
     447
River Rch & RM=whtkbrnch,Main            ,282.3
     484
Boundary for River Rch & Prof#=whtkbrnch,Main            , 1
Up Type= 0
Dn Type= 3
Dn Slope=0.022
DSS Import GetInterval= 0
DSS Import GetPeak= 0
DSS Import FillOption= 0

--- whtkbrnch.g01 (geometry) ---

Geom Title=USGS 10m DEM
Program Version=4.00

River Reach=whtkbrnch       ,Main
Reach XY= 30
     1723119.278      211804.913     1723162.764      211837.236
     1723191.075      211920.974     1723206.879      212220.273
     1723183.518      212309.563     1723183.518      212364.582
     1723198.576      212408.597     1723237.584      212454.503
     1723250.561      212598.755     1723248.863      212689.543
     1723313.341      212786.381     1723390.332      212928.949
     1723562.535      213214.591     1723621.285      213344.202
     1723691.402      213532.434     1723695.927      213591.788
     1723775.776      213755.148     1723804.434      213882.713
     1723797.244      213989.301     1723847.336      214512.604
     1723881.568      214681.507     1723905.716      214751.366
     1723952.129      214828.408     1724050.454      214956.744
     1724123.063      215077.928     1724157.076      215111.009
     1724297.246      215183.048     1724417.338      215272.395
      1724549.49      215389.649     1724697.236      215497.519

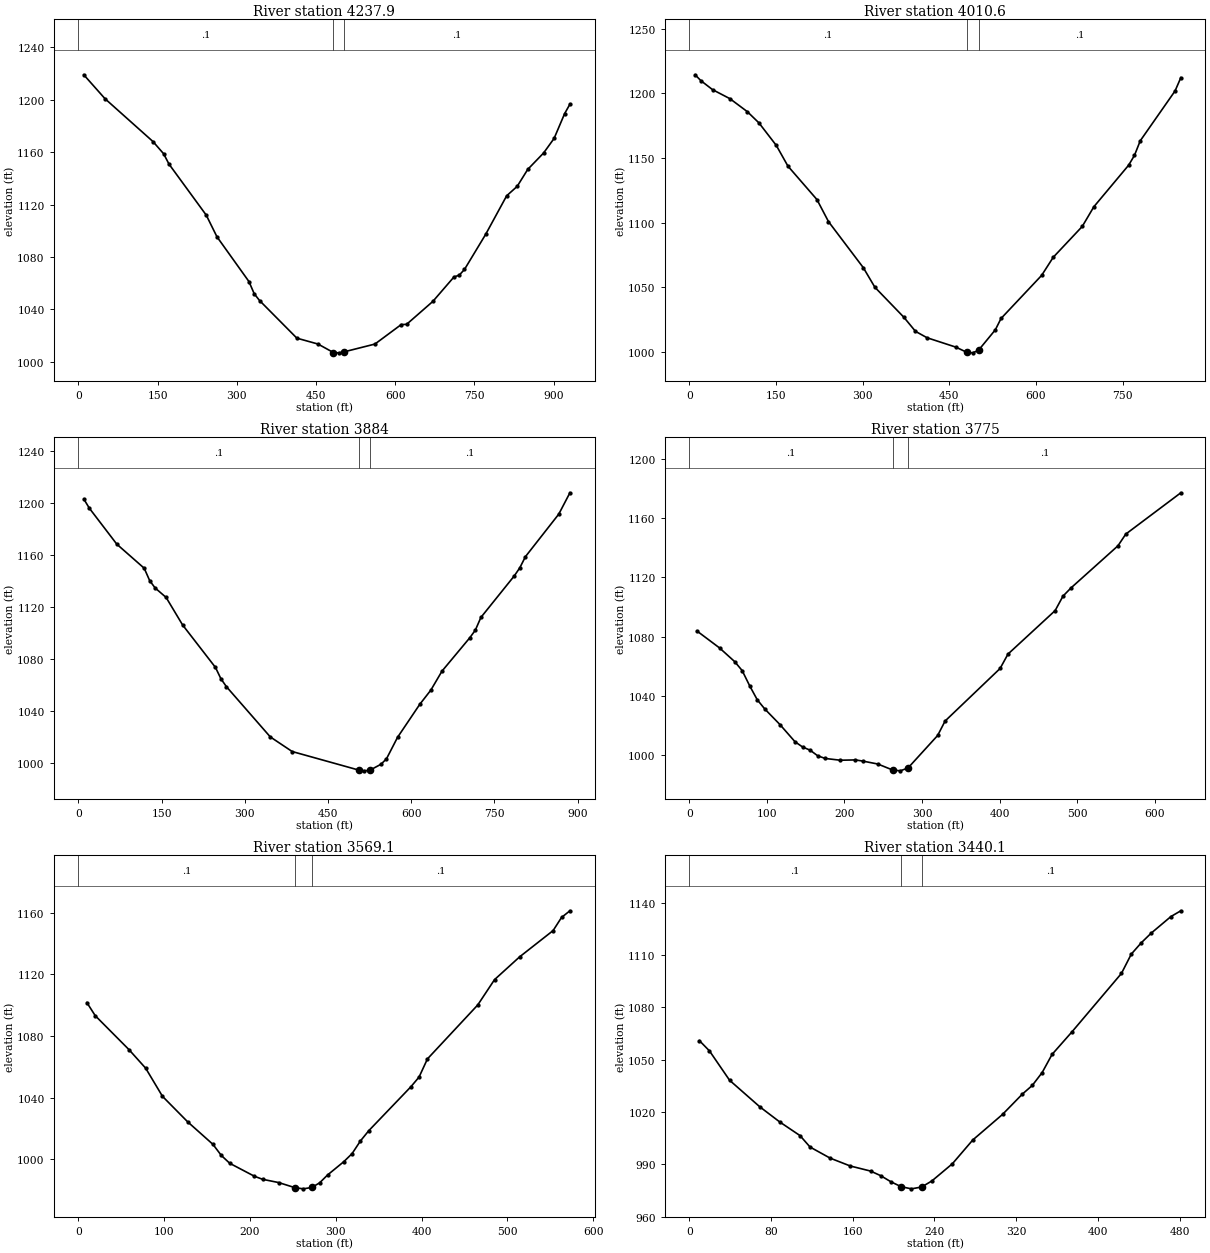
Type RM Length L Ch R = 1 ,4237.9  ,196.2,227.3,258.3
XS GIS Cut Line= 4
     1722705.222      212016.733     1723118.476      211854.587
     1723141.642      211739.336     1723093.382      211373.233
#Sta/Elev= 30
    10.1 1219.11    50.4  1200.8   141.2  1168.1   161.4 1158.76   171.5 1150.88
   242.1 1111.88   262.3 1095.38   322.9 1061.18   332.9 1051.86     343 1046.67
   413.7 1017.92   453.7 1013.43   482.9 1006.95   492.9 1006.71   502.9 1007.45
   561.5 1013.41   611.4 1028.33   621.4 1028.44   671.3 1046.03   711.2 1064.67
   721.2 1066.05   731.1  1070.4   771.1 1097.13     811 1126.68   830.9 1133.87
   850.9 1146.83   880.9 1159.35   900.8 1170.48   920.8 1189.46   930.8 1196.66
#Mann= 3 , 0 , 0
       0      .1       0   482.9    .045       0   502.9      .1       0
Bank Sta=482.9,502.9
XS Rating Curve= 0 ,0
Exp/Cntr=0.3,0.1

Type RM Length L Ch R = 1 ,4010.6  ,124.8,126.7,128.5
XS GIS Cut Line= 4
     1722709.341      212022.911      1723151.04      212020.852
     1723247.822      212006.437     1723553.613       211947.75
#Sta/Elev= 30
      10 1214.48    20.1 1209.87    40.2 1202.95    70.3 1195.95   100.4  1185.9
   120.5  1177.2   150.6 1159.71   170.7 1143.69   220.9  1117.8   240.9 1100.71
   301.2 1065.01   321.2 1049.86   371.4 1026.61   391.5 1015.69   411.6 1010.72
   461.3 1003.48   480.6   999.4   490.6  999.04   500.6 1001.03   529.8 1016.91
   539.6 1025.65   609.9 1059.05     630 1073.09   680.2 1096.96   700.3 1112.22
   760.5 1144.42   770.6 1152.02   780.6 1163.32   840.9 1201.96   850.9 1212.26
#Mann= 3 , 0 , 0
       0      .1       0   480.6    .045       0   500.6      .1       0
Bank Sta=480.6,500.6
XS Rating Curve= 0 ,0
Exp/Cntr=0.3,0.1

Type RM Length L Ch R = 1 ,3884    ,103.2,109,114.8
XS GIS Cut Line= 4
     1722707.282      212040.414     1723076.908      212149.552
     1723296.213      212133.078     1723566.998      212058.947
#Sta/Elev= 30
     9.9 1202.94    19.8 1195.98    69.2 1168.37   118.6 1149.85   128.5 1140.29
   138.3 1134.67   158.1 1127.38   187.8 1106.22   247.1 1073.51   256.9  1064.8
   266.8 1058.73   345.9 1020.06   385.4 1008.81   505.4  994.54   515.4  993.96
   525.4  994.43   545.3  998.99   555.3 1003.14   575.3 1019.72   615.4 1045.14
   635.4  1056.1   655.5 1070.71   705.6 1096.37   715.6 1102.24   725.6 1112.01
   785.8 1143.97   795.8 1150.23   805.9 1158.77     866  1191.5   886.1 1207.92
#Mann= 3 , 0 , 0
       0      .1       0   505.4    .045       0   525.4      .1       0
Bank Sta=505.4,525.4
XS Rating Curve= 0 ,0
Exp/Cntr=0.3,0.1

Type RM Length L Ch R = 1 ,3775    ,220,205.9,191.7
XS GIS Cut Line= 4
     1722978.067      212361.649     1723155.158      212241.186
     1723269.444      212258.689     1723572.146      212286.488
#Sta/Elev= 30
     9.7 1083.87    38.9 1072.42    58.4  1063.2    68.1 1057.14    77.9 1046.75
    87.6 1037.41    97.4 1031.15   116.8 1020.73   136.3 1009.09     146 1005.59
   155.8  1003.4   165.5  999.64   175.2  997.84   194.7  996.65   214.2  996.86
   223.8  996.06   243.1  994.08     262  990.09     272  989.49     282  991.43
   320.2 1013.35   329.8 1023.09   400.7 1058.53   410.9 1068.26   471.7 1097.59
   481.8 1107.33   491.9 1112.76   552.7 1141.29   562.8  1149.2   633.8 1177.07
#Mann= 3 , 0 , 0
       0      .1       0     262    .045       0     282      .1       0
Bank Sta=262,282
XS Rating Curve= 0 ,0
Exp/Cntr=0.3,0.1

Type RM Length L Ch R = 1 ,3569.1  ,118.8,129,139.2
XS GIS Cut Line= 4
      1722969.83      212497.557     1723154.128      212470.787
     1723275.621      212417.248     1723521.696      212354.442
#Sta/Elev= 30
     9.8 1101.72    19.6 1093.19    58.8 1071.27    78.4 1059.15      98 1040.92
   127.4 1024.38   156.8 1009.82   166.6 1002.61   176.4  997.53   205.2  989.13
   214.7  987.16   233.6  985.03   252.1  981.79   262.1  980.98   272.1  981.88
   281.1  984.83   290.5  989.98   309.5  998.64     319 1003.79   328.8 1012.04
   338.5 1018.67   387.4 1047.02   397.1  1053.4   406.9  1065.2   465.5 1100.12
   485.1 1116.55   514.4 1131.34   553.4 1148.35   563.2 1156.84     573 1161.18
#Mann= 3 , 0 , 0
       0      .1       0   252.1    .045       0   272.1      .1       0
Bank Sta=252.1,272.1
XS Rating Curve= 0 ,0
Exp/Cntr=0.3,0.1

Type RM Length L Ch R = 1 ,3440.1  ,234.2,224.1,214
XS GIS Cut Line= 4
     1723033.665      212611.842     1723194.283       212564.48
      1723304.45      212562.421     1723483.601      212465.639
#Sta/Elev= 30
     9.9 1060.81    19.7 1054.97    39.4 1038.14      69 1022.92    88.7 1014.17
   108.4 1006.41   118.2  999.87   137.9   993.5   157.6     989   177.5  986.09
   187.5  983.42   197.5  979.92   207.5  977.12   217.5  975.91   227.5  976.96
   237.6  980.48   257.6   990.3   277.6 1003.94   306.7 1018.57   326.1  1030.2
   335.8 1035.16   345.5 1042.56   355.2 1052.96   374.6 1065.82   423.1 1099.34
   432.8 1110.45   442.5 1116.89   452.2 1122.42   471.6 1131.97   481.3 1135.27
#Mann= 3 , 0 , 0
       0      .1       0   207.5    .045       0   227.5      .1       0
Bank Sta=207.5,227.5
XS Rating Curve= 0 ,0
Exp/Cntr=0.3,0.1

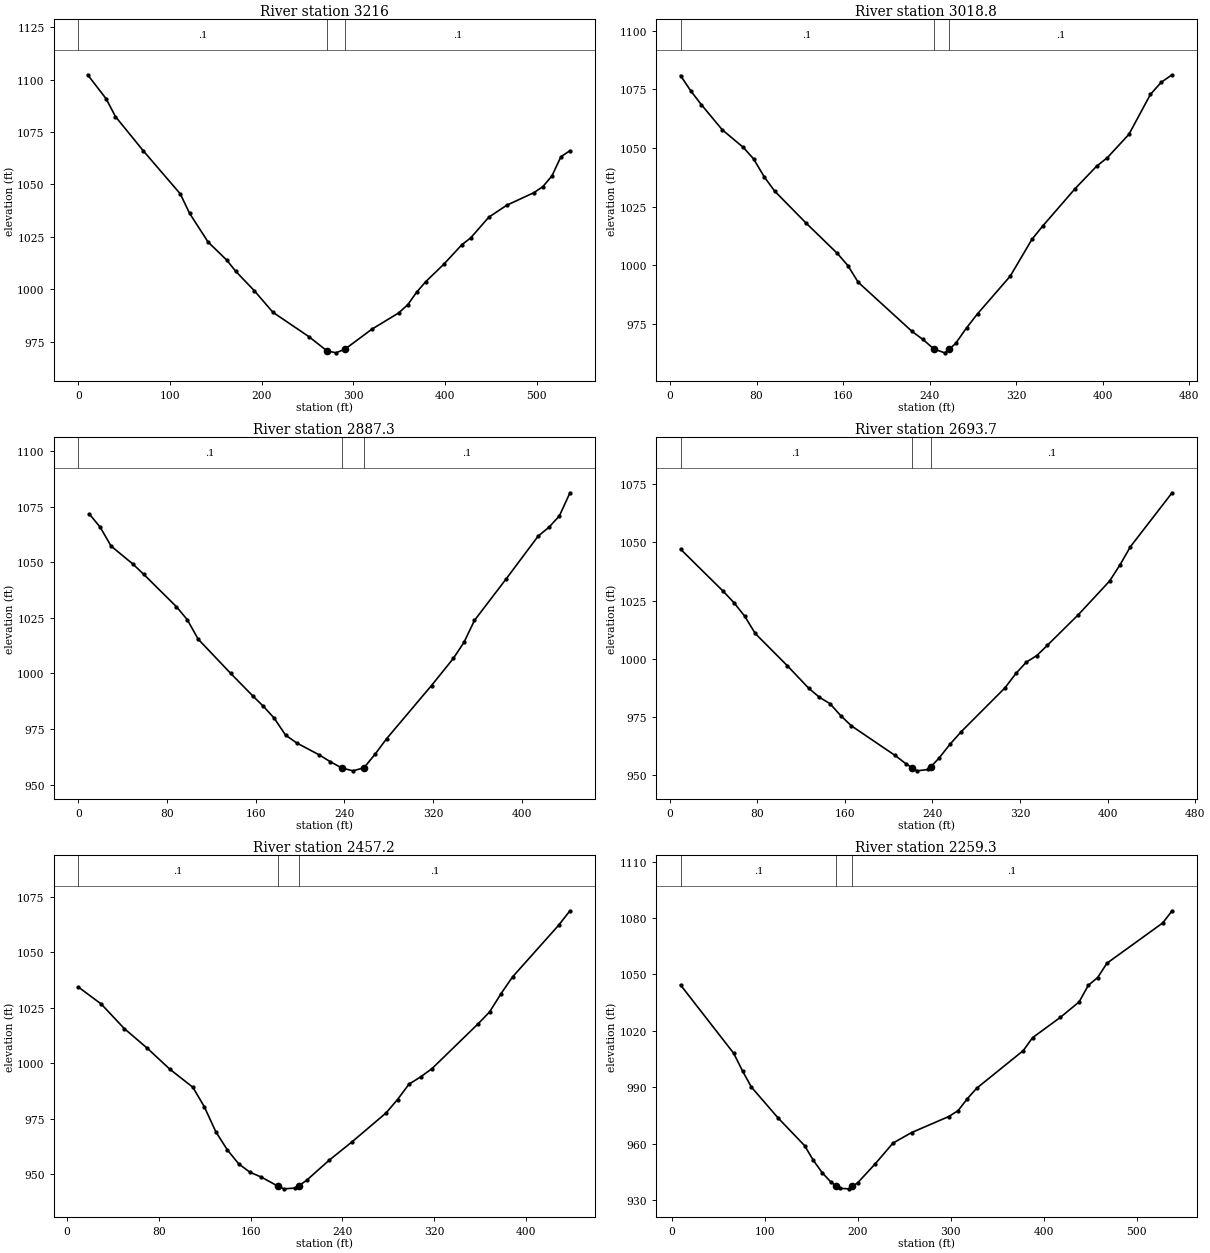
Type RM Length L Ch R = 1 ,3216    ,197.5,197.2,196.9
XS GIS Cut Line= 4
     1723062.494      212909.397      1723251.94      212793.052
     1723368.285      212741.572     1723554.643      212755.986
#Sta/Elev= 30
    10.1 1102.27    30.3 1090.78    40.4 1082.34    70.7 1066.05   111.2 1045.45
   121.3 1036.21   141.5  1022.5   161.7 1013.96   171.8 1008.48     192  999.26
   212.2  989.01   251.7  977.31     271  970.67     281  969.64     291  971.41
   320.2   980.9   349.5  988.67   359.4  992.58   369.2  998.61   379.1  1003.6
   398.7 1011.87   418.4 1021.17   428.2  1024.5   447.9 1034.36   467.6 1040.07
   497.1 1046.03   506.9 1048.92   516.8 1054.03   526.6 1063.19   536.5 1066.07
#Mann= 3 , 0 , 0
       0      .1       0     271    .045       0     291      .1       0
Bank Sta=271,291
XS Rating Curve= 0 ,0
Exp/Cntr=0.3,0.1

Type RM Length L Ch R = 1 ,3018.8  ,132,131.5,131
XS GIS Cut Line= 4
     1723180.898      213063.837     1723347.693      212966.025
     1723467.127      212911.456     1723557.732      212805.407
#Sta/Elev= 30
     9.7 1080.85    19.3 1074.26      29 1068.44    48.3 1057.74    67.7 1050.26
    77.3 1045.34      87 1037.76    96.7 1031.64   125.7 1018.03   154.7 1005.06
   164.4  999.89     174  992.76   223.7  971.84   233.8  968.39     244  964.32
     254  962.68  258.27  964.27   264.1   966.7   274.2  973.34   284.3   979.3
   314.6  995.39   334.6 1011.03   344.6 1016.73   374.5 1032.64   394.4 1042.21
   404.4 1045.88   424.3 1055.81   444.2 1072.83   454.2 1078.01   464.2 1081.19
#Mann= 3 , 0 , 0
     9.7      .1       0     244    .045       0  258.27      .1       0
Bank Sta=244,258.27
XS Rating Curve= 0 ,0
Exp/Cntr=0.3,0.1

Type RM Length L Ch R = 1 ,2887.3  ,195.2,193.6,191.9
XS GIS Cut Line= 4
     1723243.704      213161.649     1723403.292      213085.458
     1723540.229      213019.564     1723632.893       212951.61
#Sta/Elev= 30
     9.8 1071.77    19.6 1065.86    29.5  1057.3    49.1 1049.26    58.9 1044.63
    88.4 1030.06    98.2 1024.21   108.1 1015.42   137.5  999.98   157.2  989.96
     167  985.18   176.8  979.81     187  972.21   197.1  968.68   217.4  963.32
   227.5  960.22   237.8  957.42   247.8  956.15   257.8  957.56     268  963.79
   278.2  970.64   318.7  994.56   338.4 1006.75     348 1013.98   357.5 1023.88
   386.3 1042.68     415 1061.83   424.6 1065.74   434.1 1070.87   443.7 1081.31
#Mann= 3 , 0 , 0
       0      .1       0   237.8    .045       0   257.8      .1       0
Bank Sta=237.8,257.8
XS Rating Curve= 0 ,0
Exp/Cntr=0.3,0.1

Type RM Length L Ch R = 1 ,2693.7  ,234.2,236.5,238.8
XS GIS Cut Line= 4
     1723364.167      213336.681     1723516.548      213249.165
      1723639.07      213180.182     1723755.415      213097.814
#Sta/Elev= 30
     9.8 1047.14    48.8 1029.06    58.6 1024.16    68.3 1018.45    78.1 1010.93
   107.4  997.09   126.9  987.45   136.7  983.56   146.4  980.81   156.2  975.66
     166  971.27   205.9  958.58   215.9  954.97  221.38  953.34   225.9  951.99
     236  952.57  238.39  953.67     246  957.46   256.1  963.44   266.1  968.72
   306.3  987.63   316.3  993.83   325.8  998.65   335.3 1001.45   344.8 1005.79
   373.4 1019.06   401.9 1033.48   411.4 1040.46   420.9 1048.22   458.9 1071.32
#Mann= 3 , 0 , 0
     9.8      .1       0  221.38    .045       0  238.39      .1       0
Bank Sta=221.38,238.39
XS Rating Curve= 0 ,0
Exp/Cntr=0.3,0.1

Type RM Length L Ch R = 1 ,2457.2  ,198.3,197.8,197.4
XS GIS Cut Line= 4
     1723481.541      213525.098     1723615.389      213458.174
     1723723.497      213409.783     1723861.464      213309.911
#Sta/Elev= 30
      10 1034.27    29.9 1026.62    49.9  1015.6    69.8  1006.8    89.8  997.19
   109.7  989.13   119.7  980.34   129.7  969.08   139.7  960.94   149.6  954.62
   159.5  950.79   169.4  948.62  183.77  944.55   189.1  943.32     199  943.68
  202.13  944.69   208.9  947.19   228.6  956.26   248.4  964.48   278.1  977.53
   288.1  983.59   298.1  990.52   308.2  993.77   318.2  997.55   358.3  1017.7
   368.3 1023.05   378.3  1031.3   388.3 1038.83   428.4 1062.09   438.4 1068.67
#Mann= 3 , 0 , 0
      10      .1       0  183.77    .045       0  202.13      .1       0
Bank Sta=183.77,202.13
XS Rating Curve= 0 ,0
Exp/Cntr=0.3,0.1

Type RM Length L Ch R = 1 ,2259.3  ,173.6,177.6,181.6
XS GIS Cut Line= 4
      1723536.11      213684.686      1723664.81      213649.679
     1723759.534      213605.407     1724059.147      213619.821
#Sta/Elev= 30
     9.5 1044.44    66.7 1008.04    76.2  998.62    85.7  990.09   114.3  973.71
   142.9  958.92   152.4  951.03   161.9  944.46   171.4  939.42  176.89   937.5
   180.9   936.2   190.4  935.94  194.18  937.26   199.9  939.11   218.9  949.31
   237.9  960.28   257.9  965.89   297.9  974.42   307.9  977.56   317.9  983.94
   327.9   989.5   377.9 1009.47   387.9 1016.35   417.9 1027.22   437.9 1035.36
   447.9 1044.26   457.9 1048.37   467.9    1056   527.9 1077.44   537.9  1083.9
#Mann= 3 , 0 , 0
     9.5      .1       0  176.89    .045       0  194.18      .1       0
Bank Sta=176.89,194.18
XS Rating Curve= 0 ,0
Exp/Cntr=0.3,0.1

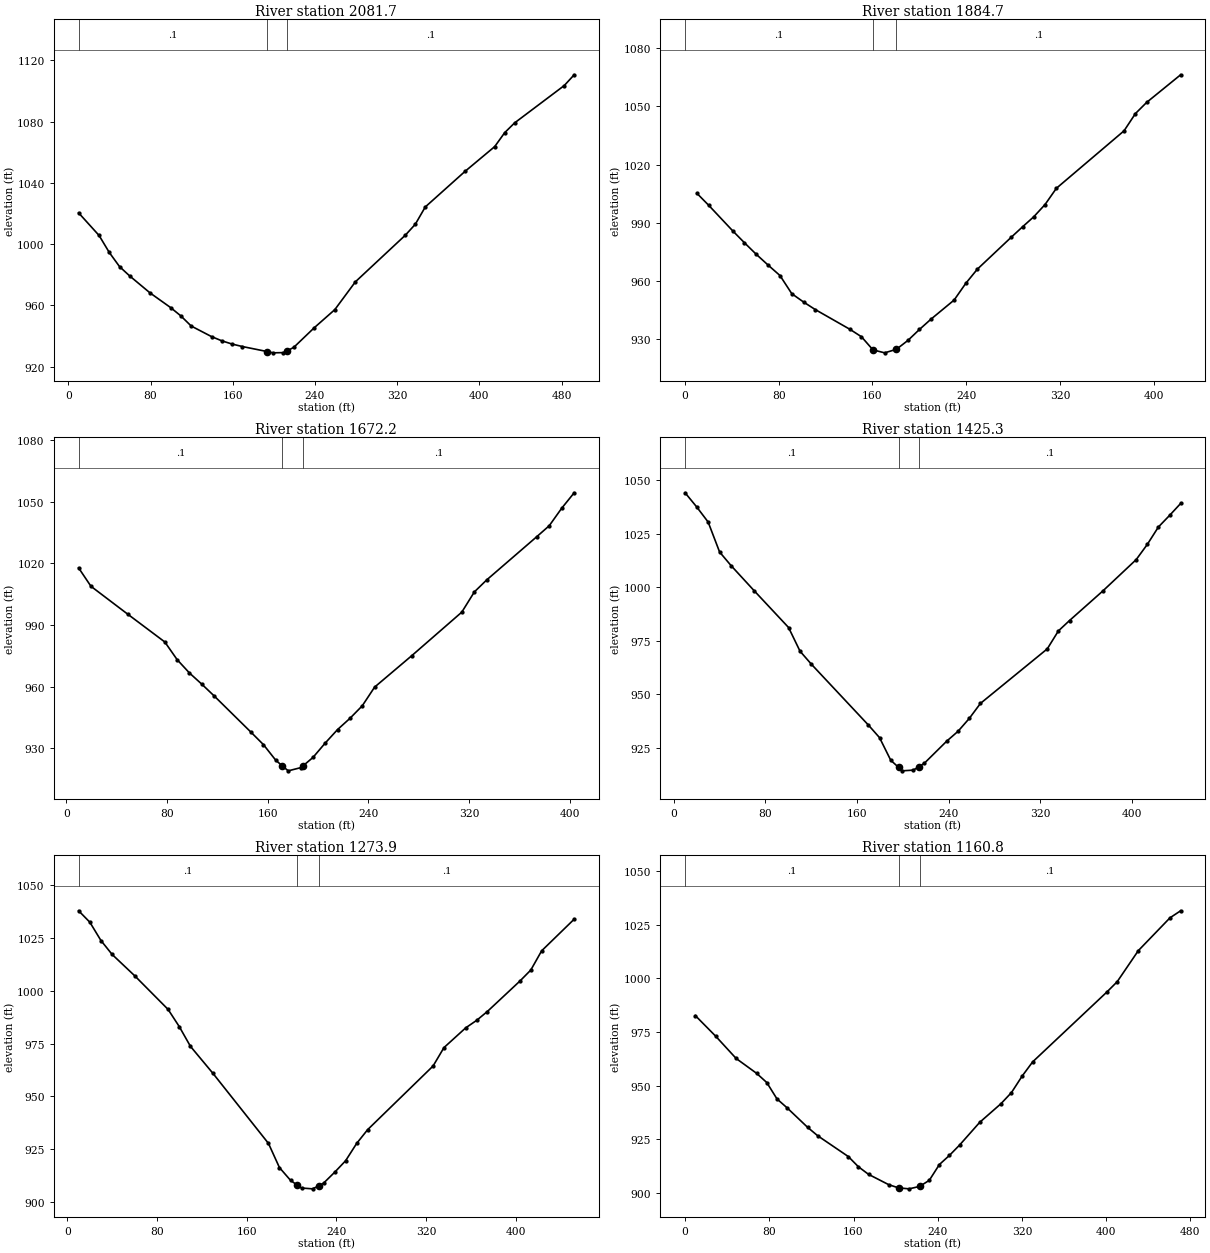
Type RM Length L Ch R = 1 ,2081.7  ,190.2,197,203.8
XS GIS Cut Line= 4
     1723581.413      213839.126      1723717.32      213808.238
     1723861.464      213767.054     1724064.362      213762.535
#Sta/Elev= 30
      10 1020.39    29.9 1005.65    39.8   994.6    49.8  985.35    59.7  979.24
    79.6  968.12    99.6  958.57   109.5  953.16   119.5  946.59   139.4  939.65
   149.4   936.9   159.4   934.8   169.4  933.18  193.66  929.89   199.3  929.08
   209.3  929.23  212.83  930.36   219.3  932.63   239.3  945.47   259.3  957.28
   279.3  975.41   327.9 1005.83   337.6 1012.96   347.3 1024.25   385.9 1047.42
   414.9 1063.66   424.6 1072.74   434.2 1079.08   482.6  1103.5   492.2  1110.5
#Mann= 3 , 0 , 0
      10      .1       0  193.66    .045       0  212.83      .1       0
Bank Sta=193.66,212.83
XS Rating Curve= 0 ,0
Exp/Cntr=0.3,0.1

Type RM Length L Ch R = 1 ,1884.7  ,214.2,212.6,210.9
XS GIS Cut Line= 4
     1723625.685      214000.773     1723725.557        213984.3
     1723873.819       213983.27     1724045.762      213959.589
#Sta/Elev= 30
    10.1 1005.13    20.2  998.93    40.5  985.88    50.6  979.68    60.7  973.72
    70.9   968.1      81  962.73    91.1  953.36   101.2  949.04   111.1  945.19
   140.8  934.96   150.6  931.14   160.4  924.38   170.4  922.85   180.4  924.67
   190.2  929.23   200.1  934.91   209.9   940.2   229.7  950.08   239.6  958.65
   249.5  965.99   278.4  982.44   288.1  987.84   297.7  993.04   307.3  999.33
     317 1007.72   374.8 1037.39   384.5 1046.28   394.1 1052.05   423.1 1066.29
#Mann= 3 , 0 , 0
       0      .1       0   160.4    .045       0   180.4      .1       0
Bank Sta=160.4,180.4
XS Rating Curve= 0 ,0
Exp/Cntr=0.3,0.1

Type RM Length L Ch R = 1 ,1672.2  ,249,246.9,244.8
XS GIS Cut Line= 4
     1723634.952      214205.664     1723732.764      214201.545
     1723889.263       214190.22     1724035.466       214162.42
#Sta/Elev= 29
     9.8 1017.75    19.6  1008.8    48.9  995.19    78.3  981.68    88.1  973.07
    97.9  966.57   107.7  961.13   117.5  955.42   146.9  937.68   156.7  931.68
   166.5  924.07  171.46  921.46   176.4  918.94   186.2  920.48  187.81  921.22
     196  925.44   205.8   932.5   215.6  939.06   225.4  944.49   235.2  950.61
     245   959.7   274.7   975.1   314.3  996.22   324.3 1006.08   334.2 1011.97
   373.9 1032.97   383.8  1038.3   393.7 1046.83   403.6 1054.34
#Mann= 3 , 0 , 0
     9.8      .1       0  171.46    .045       0  187.81      .1       0
Bank Sta=171.46,187.81
XS Rating Curve= 0 ,0
Exp/Cntr=0.3,0.1

Type RM Length L Ch R = 1 ,1425.3  ,153.1,151.3,149.5
XS GIS Cut Line= 4
     1723634.952      214444.531     1723785.273      214449.679
     1723910.885      214430.117     1724072.532      214397.169
#Sta/Elev= 30
      10 1044.03    20.1 1037.44    30.1 1030.39    40.1 1016.41    50.1 1010.06
    70.2  998.38   100.3  981.17   110.3  970.12   120.3  963.99     170  935.64
   179.7  929.78   189.5  919.22  196.39  915.88   199.3  914.29   209.1  914.62
  214.11  916.21   218.9  917.88   238.4  928.17   248.2  932.73     258  938.72
   267.8  945.76   326.1   971.2   335.8  979.57   345.5  984.41   374.6  998.22
   403.7 1012.84   413.4 1019.93   423.1 1028.07   432.8 1033.44   442.5 1039.04
#Mann= 3 , 0 , 0
      10      .1       0  196.39    .045       0  214.11      .1       0
Bank Sta=196.39,214.11
XS Rating Curve= 0 ,0
Exp/Cntr=0.3,0.1

Type RM Length L Ch R = 1 ,1273.9  ,114.1,113.1,112.1
XS GIS Cut Line= 4
     1723652.455      214635.007     1723808.954       214603.09
     1723933.536      214574.261     1724086.946      214514.544
#Sta/Elev= 30
      10 1037.98      20 1032.56    29.9 1023.88    39.9 1017.26    59.9 1007.22
    89.8  991.21    99.8  983.04   109.8  973.66   129.8   960.9   179.4  927.63
   189.2  916.16   199.1  910.11  204.74  907.95   208.9  906.47   218.7  906.08
  224.55  907.57   228.6   908.8   238.4  913.91   248.2  919.38   258.1  927.62
   267.9  934.15   326.3  964.35     336  973.07   355.4  982.44   365.1  985.97
   374.7  990.19   403.8 1004.65   413.5 1009.87   423.2    1019   452.2 1033.99
#Mann= 3 , 0 , 0
      10      .1       0  204.74    .045       0  224.55      .1       0
Bank Sta=204.74,224.55
XS Rating Curve= 0 ,0
Exp/Cntr=0.3,0.1

Type RM Length L Ch R = 1 ,1160.8  ,208.2,201.5,194.8
XS GIS Cut Line= 4
     1723680.254       214729.73     1723834.694      214715.316
     1723955.158      214682.369     1724092.094       214549.55
#Sta/Elev= 30
     9.7  982.69    29.1  973.06    48.5   962.7    67.9  955.79    77.6  951.49
    87.3  943.85    96.9   939.7   116.3  930.66     126  926.68   155.1  916.98
   164.7  912.22   174.3   908.7   193.5  903.88   202.8   902.4   212.8  901.95
   222.8  903.08     232  905.92   241.6  913.28   251.2  917.56   260.8  922.36
     280  932.99   300.1  941.62   310.1  946.83   320.2  954.48   330.2  961.11
   400.5  993.56   410.5  998.45   430.6 1012.95   460.7 1028.25   470.8 1031.52
#Mann= 3 , 0 , 0
       0      .1       0   202.8    .045       0   222.8      .1       0
Bank Sta=202.8,222.8
XS Rating Curve= 0 ,0
Exp/Cntr=0.3,0.1

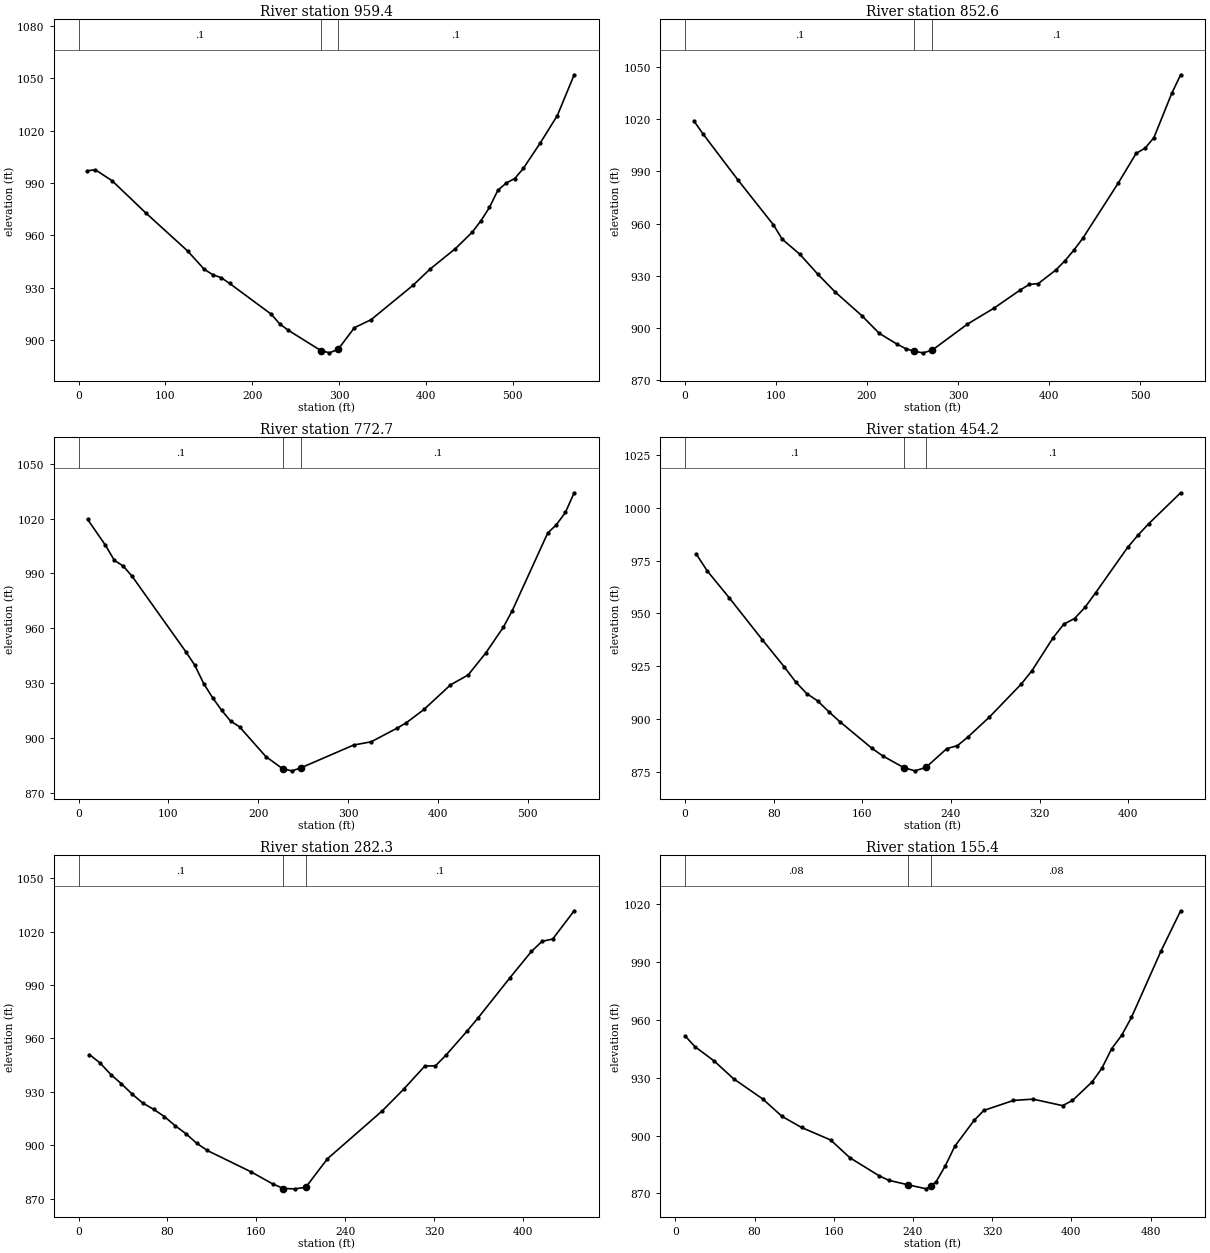
Type RM Length L Ch R = 1 ,959.4   ,112.6,106.7,100.9
XS GIS Cut Line= 4
     1723760.563      215054.054     1723911.914      214919.177
     1724043.703      214840.927     1724224.913      214725.612
#Sta/Elev= 30
     9.7  997.01    19.3  997.58    38.6   991.3    77.2  972.94   125.5  951.07
   144.8  940.49   154.5  937.45   164.1  935.75   173.8  932.48   221.9  914.79
   231.5  909.31     241  905.76   278.9  893.97   288.9  892.65   298.9  894.68
   317.7  907.08   336.8  911.62   385.3  931.43   404.8  940.67   434.1  952.44
   453.6  961.93   463.4  968.38   473.2  976.02   482.9  985.85   492.7  990.05
   502.4   992.6   512.2  998.35   531.7 1012.95   551.3 1028.59   570.8 1052.07
#Mann= 3 , 0 , 0
       0      .1       0   278.9    .045       0   298.9      .1       0
Bank Sta=278.9,298.9
XS Rating Curve= 0 ,0
Exp/Cntr=0.3,0.1

Type RM Length L Ch R = 1 ,852.6   ,81,80,78.9
XS GIS Cut Line= 4
     1723868.671      215140.541     1723992.223      215016.989
     1724110.627      214902.703     1724229.031      214734.878
#Sta/Elev= 30
     9.7 1019.08    19.4 1011.77    58.2  985.02    97.1  959.31   106.8  951.01
   126.2  942.37   145.6  931.09     165  920.68   194.1  907.17   213.4  896.94
   232.8  890.77   242.5  888.15   251.8  886.56   261.8  885.72   271.8  887.33
   310.3  902.22   339.3  911.33   368.6  921.93   378.4  925.03   388.2  925.55
   407.8  933.45   417.5  938.65   427.3  944.73   437.1  951.55   476.2   983.4
   495.8 1000.41   505.6 1003.37   515.3 1009.43   534.9 1034.87   544.7 1045.58
#Mann= 3 , 0 , 0
       0      .1       0   251.8    .045       0   271.8      .1       0
Bank Sta=251.8,271.8
XS Rating Curve= 0 ,0
Exp/Cntr=0.3,0.1

Type RM Length L Ch R = 1 ,772.7   ,321.8,318.4,315.1
XS GIS Cut Line= 4
     1723929.418      215193.051     1724056.058       215066.41
     1724184.758      214932.562     1724247.564        214756.5
#Sta/Elev= 30
     9.9 1019.58    29.8 1005.47    39.8  997.15    49.7  994.06    59.7  988.38
   119.4  947.25   129.3  939.94   139.3  929.86   149.2  922.16   159.2  915.35
   169.1   909.5   179.1  906.33   208.4  890.08   227.7  883.23   237.7  882.29
   247.7  883.97   306.1  896.36   325.7  898.14     355   905.7   364.8  908.52
   384.5  915.79     414  929.19   433.7  934.63   453.3  946.62     473  960.81
   482.8  969.74   522.2 1012.03     532 1016.67   541.9 1023.31   551.7 1034.05
#Mann= 3 , 0 , 0
       0      .1       0   227.7    .045       0   247.7      .1       0
Bank Sta=227.7,247.7
XS Rating Curve= 0 ,0
Exp/Cntr=0.3,0.1

Type RM Length L Ch R = 1 ,454.2   ,171.5,171.9,172.2
XS GIS Cut Line= 4
     1724186.818      215359.846     1724304.192      215267.182
     1724383.471      215158.044     1724455.543      215011.841
#Sta/Elev= 30
      10  978.16    19.9  970.19    39.9  957.39    69.8  937.54    89.7  924.67
    99.7  917.74   109.7  912.18   119.6  908.72   129.6  903.65   139.6  898.92
   168.8  886.24   178.4   882.7   197.4  877.16   207.4  875.63   217.4  877.24
   236.3  886.15   245.9  887.54   255.5   891.7   274.8  901.08   303.6  916.71
   313.2  923.01   332.4  938.65     342     945   351.6  947.62   361.1  952.95
   370.7  959.83   399.5  981.21   409.1  987.14   418.7   992.5   447.4 1007.06
#Mann= 3 , 0 , 0
       0      .1       0   197.4    .045       0   217.4      .1       0
Bank Sta=197.4,217.4
XS Rating Curve= 0 ,0
Exp/Cntr=0.3,0.1

Type RM Length L Ch R = 1 ,282.3   ,125.7,126.9,128.2
XS GIS Cut Line= 4
     1724329.932      215437.066      1724438.04      215373.231
     1724526.586      215254.827     1724558.504      215084.943
#Sta/Elev= 30
     9.7   950.9    19.3   946.2      29  939.69    38.6  934.44    48.3  928.63
    57.9  923.61    67.6  920.11    77.3  916.03    86.9  910.92    96.6  906.46
   106.2  901.11   115.9  896.98   155.1  885.05   174.8  878.19   184.5   875.6
   194.5  875.43   204.5  876.26   224.1  892.34   273.4  919.22   292.6  931.33
   311.8  944.45   321.4  944.59     331  950.66   350.2  964.35   359.8  971.54
   388.6  994.18   407.8 1008.88   417.4 1014.54     427 1015.86   446.3 1031.72
#Mann= 3 , 0 , 0
       0      .1       0   184.5    .045       0   204.5      .1       0
Bank Sta=184.5,204.5
XS Rating Curve= 0 ,0
Exp/Cntr=0.3,0.1

Type RM Length L Ch R = 1 ,155.4   ,103.5,104.2,104.9
XS GIS Cut Line= 4
     1724334.565      215438.224     1724550.009      215432.047
     1724598.658      215373.359     1724661.978      215164.093
#Sta/Elev= 30
     9.8  951.73    19.6  946.21    39.2  938.68    58.8  929.47    88.2  918.99
   107.8  909.92   127.4   904.2   156.8  897.71   176.3  888.48   205.7  879.16
   215.5  876.79   234.6  874.49   253.6  872.35  257.74  873.85   263.2  875.87
   272.7  884.34   282.2   894.4   301.7  907.83   311.6  913.04   341.5  918.23
   361.3   918.9   391.1  915.53   401.1  918.21     421  927.85   430.9  934.96
   440.8  945.15   450.8     952   460.7  961.31   490.5  995.69   510.4 1016.65
#Mann= 3 , 0 , 0
     9.8     .08       0   234.6    .045       0  257.74     .08       0
Bank Sta=234.6,257.74
XS Rating Curve= 0 ,0
Exp/Cntr=0.3,0.1

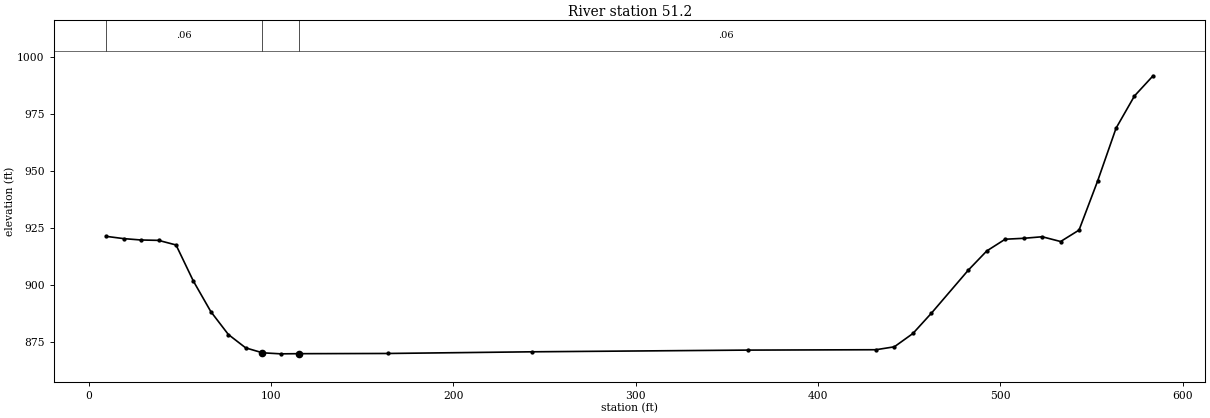
Type RM Length L Ch R = 1 ,51.2    ,53.4,51.2,49
XS GIS Cut Line= 4
     1724457.081      215547.713     1724581.406      215552.346
     1724750.517      215359.295     1724739.707      215156.979
#Sta/Elev= 30
     9.6   921.3    19.1  920.31    28.7   919.7    38.3  919.54    47.9  917.52
    57.4   901.7      67  888.28    76.6  878.27    86.1  872.41    95.3  870.26
   105.3   869.8   115.3  869.87   163.9  869.96   242.9  870.69   361.3  871.44
   431.7   871.6   441.8  872.88     452  878.72   462.1  887.58   482.4  906.51
   492.5   914.9   502.6  920.04   512.7  920.44   522.9  921.12     533  919.03
   543.1  924.04   553.3  945.57   563.4  968.71   573.5  982.84   583.7  991.68
#Mann= 3 , 0 , 0
     9.6     .06       0    95.3    .045       0   115.3     .06       0
#XS Ineff= 2 , 0
       0                     200       0
Permanent Ineff=
       F       F
Bank Sta=95.3,115.3
XS Rating Curve= 0 ,0
Exp/Cntr=0.3,0.1

Chan Stop Cuts=-1
Use User Specified Reach Order=0